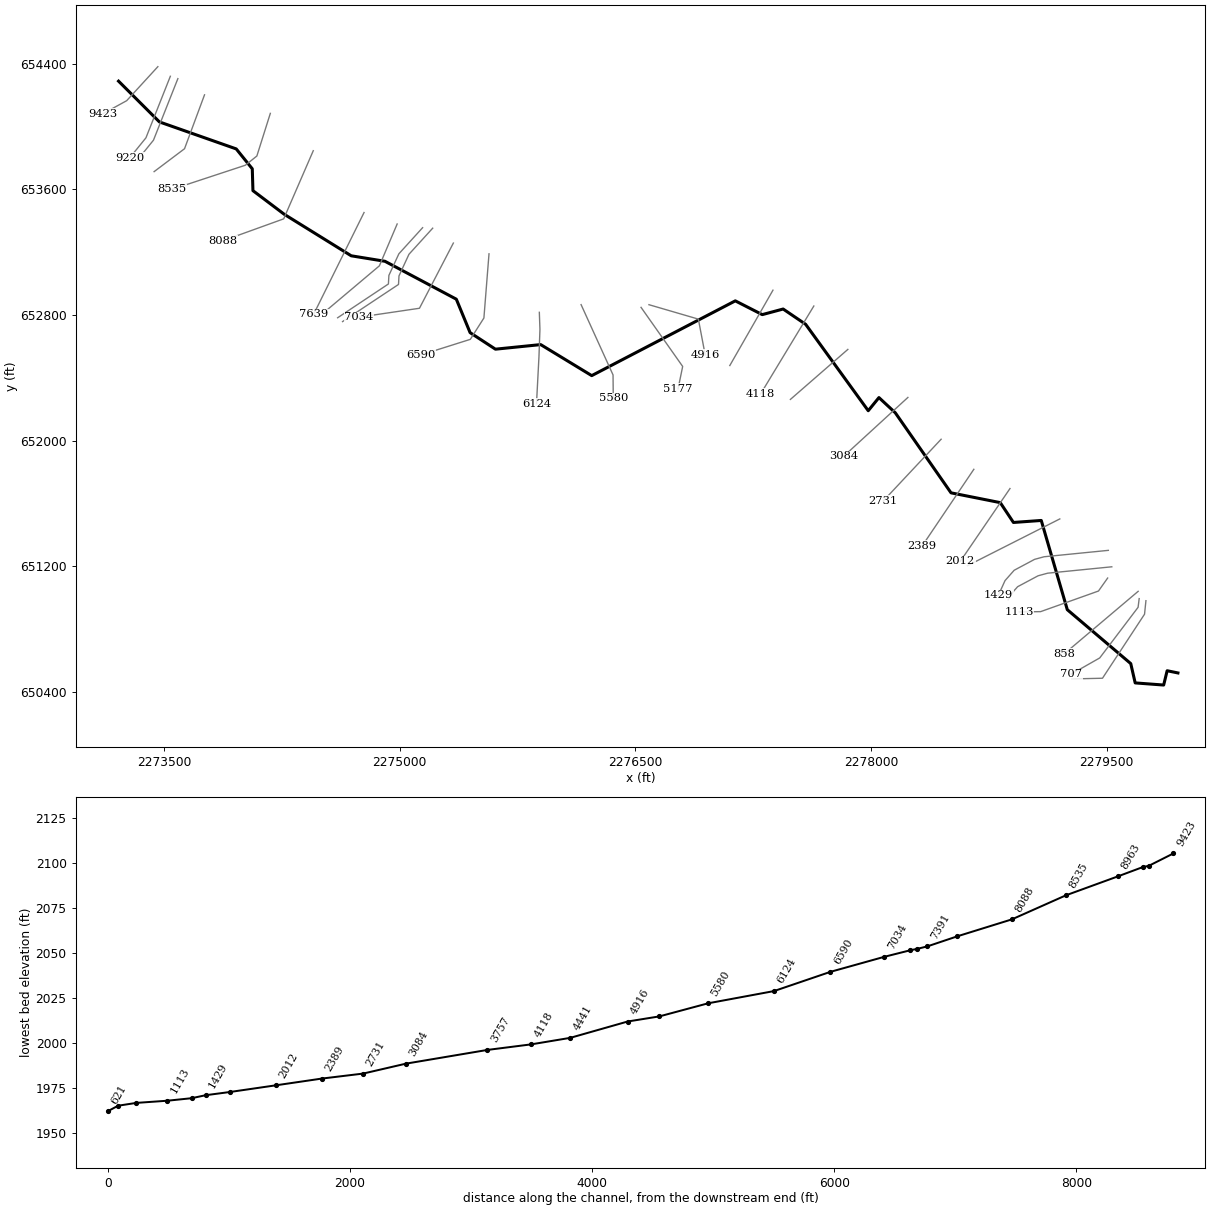
--- TYGVRVT2.prj (project) ---

Proj Title=TYGVRVT2
Current Plan=p01
Default Exp/Contr=0,0
English Units
Geom File=g01
Flow File=f01
Plan File=p01
BEGIN DESCRIPTION:
----------MODEL BY WOOD PLC 2022----------
AFH study
Randolph County, WV
HEC-RAS Version: RAS 6.2
Vertical Datum: NAVD88
Projection: NAD 1983 StatePlane West Virginia S FIPS 4702 (US Feet)
Terrain: 1-meter LIDAR (FEMA Region III 3DEP collected 2016-2018)
Land Use: 2019 NLCD
Hydrologic Method:
WV SIR2010-5033 regression equations
Additional Model Notes:
DS extent is dominated by main stem backwater
END DESCRIPTION:
DSS Export Rating Curves= 0
DSS Export Rating Curve Sorted= 0
DSS Export Volume Flow Curves= 0
DXF OffsetX= 0
DXF OffsetY= 0
DXF ScaleX= 0
DXF ScaleY= 0

--- TYGVRVT2.p01 (plan) ---

Plan Title=Floodplain
Program Version=6.20
Short Identifier=Floodplain
Geom File=g01
Flow File=f01
Subcritical Flow
K Sum by GR= 0
Std Step Tol= 0.01
Critical Tol= 0.01
Num of Std Step Trials= 20
Max Error Tol= 0.3
Flow Tol Ratio= 0.001
Split Flow NTrial= 30
Split Flow Tol= 0.02
Split Flow Ratio= 0.02
Log Output Level= 0
Friction Slope Method= 1
Unsteady Friction Slope Method= 2
Unsteady Bridges Friction Slope Method= 1
Parabolic Critical Depth
Global Vel Dist= 0 , 0 , 0
Global Log Level= 0
CheckData=True
Encroach Param=-1 ,0,0, 0
Mapping Interval=1HOUR
Computation Time Step Use Courant=        0
Computation Time Step Use Time Series=    0
Computation Time Step Count To Double=0
Computation Time Step Max Doubling=0
Computation Time Step Max Halving=0
Computation Time Step Residence Courant=0
Run HTab= 0
Run UNet= 0
Run Sediment= 0
Run PostProcess= 0
Run WQNet= 0
Run RASMapper=-1
UNET Theta= 0
UNET Theta Warmup= 0
UNET ZTol= 0
UNET ZSATol= 0
UNET MxIter= 0
UNET Max Iter WO Improvement= 0
UNET MaxInSteps= 0
UNET DtIC= 0
UNET DtMin= 0
UNET MaxCRTS= 0
UNET WFStab= 0
UNET SFStab= 0
UNET WFX= 1
UNET SFX= 1
UNET Gravity=32.174
UNET 1D Methodology=Finite Difference
UNET DSS MLevel= 1
UNET Pardiso=0
UNET DZMax Abort= 0
UNET Use Existing IB Tables= 0
UNET Froude Reduction=False
UNET Froude Limit= 0
UNET Froude Power= 0
UNET D1 Cores= 0
UNET WindReference=Eulerian
UNET WindDragFormulation=Hsu (1988)
UNET D2 Coriolis=0
UNET D2 Cores= 0
UNET D2 Theta= 1
UNET D2 Theta Warmup= 1
UNET D2 Z Tol= 0.01
UNET D2 Volume Tol= 0.01
UNET D2 Max Iterations= 20
UNET D2 Equation= 0
UNET D2 RampUpFraction=0.1
UNET D2 TimeSlices= 1
UNET D2 Turbulence Formulation=Non-Conservative (original)
UNET D2 Smagorinsky Mixing=0
UNET D2 BCVolumeCheck=0
UNET D2 Cores=0
UNET D2 SolverType=PARDISO (Direct)
UNET D2 Minimum Iterations= 2147483647
UNET D2 Maximum Iterations= 2147483647
UNET D2 Restart Number= 10
UNET D2 Relaxation Coeff=1.3
UNET D2 SOR Precondition Iterations= 10
UNET D2 ILUT Maximum Fill= 8
UNET D2 ILUT Tolerance=1E-08
UNET D1D2 MaxIter= 0
UNET D1D2 ZTol=0.01
UNET D1D2 QTol=0.1
UNET D1D2 MinQTol=1
Write IC File= 0
Write IC File at Fixed DateTime=0
Write IC File at Sim End=0
Echo Input=False
Echo Parameters=False
Echo Output=False
Write Detailed= 0
HDF Write Warmup=0
HDF Write Time Slices=0
HDF Flush=0
HDF Compression= 1
HDF Chunk Size= 1
HDF Spatial Parts= 1
HDF Use Max Rows=0
HDF Fixed Rows= 1
Calibration Method= 0
Calibration Iterations= 20
Calibration Max Change=0.05
Calibration Tolerance=0.2
Calibration Maximum=1.5
Calibration Minimum=0.5
Calibration Optimization Method= 1
WQ AD Non Conservative
WQ ULTIMATE=-1
WQ Max Comp Step=1HOUR
WQ Output Interval=15MIN
WQ Output Selected Increments= 0
WQ Output face flow=0
WQ Output face velocity=0
WQ Output face area=0
WQ Output face dispersion=0
WQ Output cell volume=0
WQ Output cell surface area=0
WQ Output cell continuity=0
WQ Output cumulative cell continuity=0
WQ Output face conc=0
WQ Output face dconc_dx=0
WQ Output face courant=0
WQ Output face peclet=0
WQ Output face adv mass=0
WQ Output face disp mass=0
WQ Output cell mass=0
WQ Output cell source sink temp=0
WQ Output nsm pathways=0
WQ Output nsm derived pathways=0
WQ Create Restart=0
WQ Fixed Restart=0
WQ System Summary=0
WQ Write To DSS=0
Sorting and Armoring Iterations= 10
XS Update Threshold= 0.02
Bed Roughness Predictor= 0
Hydraulics Update Threshold= 0.02
Energy Slope Method= 1
Volume Change Method= 1
Sediment Retention Method= 0
Sediment TS Multiplier= 1
Warm Up Method= 0
XS Weighting Method= 0
Number of US Weighted Cross Sections= 1
Number of DS Weighted Cross Sections= 1
Upstream XS Weight=0
Main XS Weight=1
Downstream XS Weight=0
Number of DS XS's Weighted with US Boundary= 1
Upstream Boundary Weight= 1
Weight of XSs Associated with US Boundary= 0
Number of US XS's Weighted with DS Boundary= 1
Downstream Boundary Weight= 0.5
Weight of XSs Associated with DS Boundary= 0.5
Percentile Method= 0
Sediment Output Level= 3
Mass or Volume Output= 0
Output Increment Type= 1
Profile and TS Output Increment= 1
Transport Output Increment 1
XS Output Flag= 0
XS Output Increment= 10
Read HDF5 Sediment Hotstart= 0
Sediment Hotstart Type= 0
Write Gradation File= 0
Read Gradation Hotstart= 0
Write HDF5 File= 1
Write Binary Output= 1
Write DSS Sediment File= 0
DSS Sediment Output Type= 1
SV Curve= 0
Specific Gage Flag= 0
Subcell Erosion Methods= 0
Subcell Deposition Methods= 0
Advection Scheme= 1
Matrix Solver= 0
Implicit Weighting Factor= 1
Maximum Outer Loop Convergence Iterations= 5
Convergence Maximum Absolute= 0.001
Convergence RMSE= 0.0001
Grain Fractions Max Abs Error= 0.001
Max Subgrid Regions= 1
Max Subgrid Length Scale= 3.402823E+38
Initial Layer Thickness= 3.402823E+38
Min Layer Thickness= 3.402823E+38
Max Layer Thickness= 3.402823E+38
Number of Layers= 5

--- TYGVRVT2.f01 (steady flow) ---

Flow Title=Flow
Program Version=6.20
Number of Profiles= 1
Profile Names=P100yr
River Rch & RM=TYGVRVT2,Main,9423
     337
River Rch & RM=TYGVRVT2,Main,6590
     412
River Rch & RM=TYGVRVT2,Main,5177
     601
Boundary for River Rch & Prof#=TYGVRVT2,Main            , 1
Up Type= 0
Dn Type= 3
Dn Slope=0.00876
DSS Import GetInterval= 0
DSS Import GetPeak= 0
DSS Import FillOption= 0

--- TYGVRVT2.g01 (geometry) ---

Geom Title=Geometry
Program Version=6.20

River Reach=TYGVRVT2        ,Main
Reach XY= 30
     2273211.663      654287.829     2273471.559      654028.454
     2273960.622      653856.579     2274062.705      653730.016
     2274066.872      653590.954     2274266.351      653440.433
     2274692.392       653176.37     2274906.976      653141.475
     2275361.142      652900.329     2275448.864      652687.387
     2275610.101      652582.099     2275898.122      652611.266
 2276222.8644727652413.8213387312277136.57834989 652889.64643001
      2277308.22      652802.024     2277441.051       652837.63
2277584.03480549652740.621987799     2277982.579      652190.474
     2278050.668       652274.092278154.72312901652177.380835423
     2278509.377      651667.916     2278822.794      651605.543
     2278906.609      651479.362      2279083.67      651492.138
     2279249.404      650924.2192279653.23597741650581.126034644
     2279681.395      650458.273     2279862.634      650444.729
2279884.81778856650535.7428158622279953.38800377650521.683048953

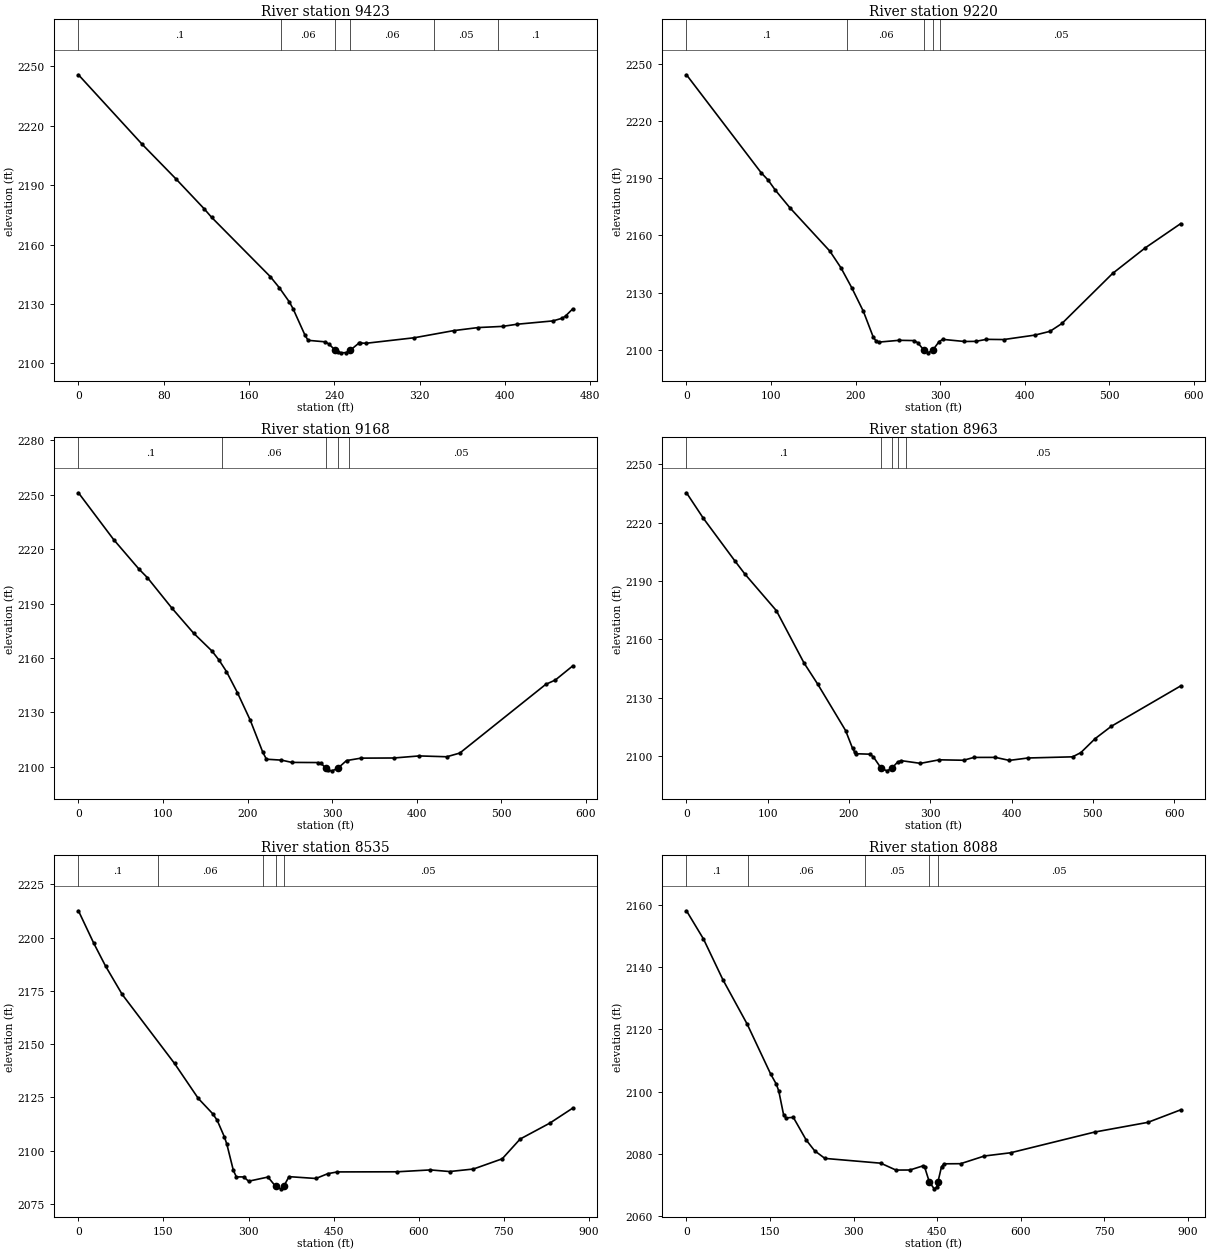
Type RM Length L Ch R = 1 ,9423    ,201.6,203.3,205.2
XS GIS Cut Line= 3
2273461.76939252654379.9656500122273263.30989027654163.466146434
2273114.47955877654081.691586581
#Sta/Elev= 30
       0 2245.77    59.7 2210.69    91.2 2193.31   117.7  2178.2   124.8 2173.81
   179.9 2143.82   188.3 2138.27   197.7 2131.09   201.3 2127.58   212.6 2114.07
   215.4 2111.63   231.7 2110.85   235.3 2109.56   240.9 2106.57   243.7 2105.61
   246.6 2105.31     251 2105.44  254.86 2106.61   262.8 2110.11   264.2  2110.3
   269.7 2110.14   315.1 2112.94     352 2116.54   374.9 2118.08   397.7 2118.67
   411.4 2119.76     445 2121.44   453.8 2122.81   456.8 2123.91   463.5 2127.49
#Mann= 6 ,-1,0
       0      .1       0     190     .06       0   240.9    .045       0
  254.86     .06       0   333.7     .05       0   393.7      .1       0
Bank Sta=240.9,254.86
XS Rating Curve= 0 ,0
Exp/Cntr=0.3,0.1

Type RM Length L Ch R = 1 ,9220    ,50.9,51.3,51.4
XS GIS Cut Line= 3
2273541.24639365654318.8862937452273385.99392747653927.186106078
 2273283.3845389653800.485817584
#Sta/Elev= 30
       0  2244.2    88.4  2192.8    96.5 2189.02   105.1  2183.7   122.3 2174.47
   169.6 2151.71   182.6 2143.05   195.5 2132.49   209.2 2120.15   220.9 2106.62
     224 2104.75   227.1 2104.04   251.4    2105   268.6 2104.86   273.3 2103.79
  280.57 2099.95   285.6 2098.43  291.37 2099.95   298.7 2104.32     303 2105.49
   328.6 2104.38   341.8 2104.44   354.7  2105.5     375 2105.39     412 2107.73
   429.8  2109.7     444 2113.83   503.8 2140.03   542.3 2153.41584.3847 2166.18
#Mann= 5 ,-1,0
       0      .1       0     190     .06       0  280.57    .045       0
  291.37     .06       0     300     .05       0
Bank Sta=280.57,291.37
XS Rating Curve= 0 ,0
Exp/Cntr(USF)=0,0
Exp/Cntr=0.3,0.1

Type RM Length L Ch R = 1 ,9168    ,205.3,205.8,205.7
XS GIS Cut Line= 3
2273589.12444836654303.8425341532273433.87198218653912.142346486
2273331.26259361653785.442057992
#Sta/Elev= 30
       0  2251.1    41.6  2225.3    71.7 2208.93    81.5  2204.3   110.4 2187.53
   136.2 2173.64   157.8 2163.84   166.4 2158.71     175 2152.49   187.9 2140.91
   203.1 2125.69     218 2107.94   222.3  2104.1   240.1  2103.6   252.4 2102.34
   283.2 2102.26   286.8 2101.82  293.03 2099.02   295.5    2098   299.8 2097.69
   306.5 2099.02     317 2103.36   334.2  2104.7   372.9 2104.78     403 2105.92
   435.5 2105.46   450.9 2107.49   552.6 2145.41   563.9 2147.79   584.4 2155.55
#Mann= 5 ,-1,0
       0      .1       0     170     .06       0  293.03    .045       0
   306.5     .06       0     320     .05       0
Bank Sta=293.03,306.5
XS Rating Curve= 0 ,0
Exp/Cntr(USF)=0,0
Exp/Cntr=0.3,0.1

Type RM Length L Ch R = 1 ,8963    ,430.7,427.4,423.1
XS GIS Cut Line= 3
2273758.72135506 654200.721290012273631.56916664653857.799695737
2273437.92876092 653711.98673176
#Sta/Elev= 30
       0  2235.3    20.8 2222.18    59.2 2200.51      72 2193.51   110.6 2174.78
   144.6 2147.93   161.6 2136.96   195.8  2113.2   204.3 2104.11     207 2102.11
   208.6 2101.31   225.7 2101.08   229.9 2099.73  239.72 2093.75   246.9 2092.53
   252.6 2093.85   259.7 2096.99     264 2097.77   287.9 2096.37   310.9 2098.19
   340.9 2097.97   353.6 2099.42   380.1 2099.44   397.2 2097.89   420.3 2099.13
   475.1 2099.72   485.2 2101.88   502.9 2109.09   522.8 2115.42   608.1 2136.14
#Mann= 5 ,-1,0
       0      .1       0  239.72    .045       0   252.6      .1       0
     260     .06       0     270     .05       0
Bank Sta=239.72,252.6
XS Rating Curve= 0 ,0
Exp/Cntr=0.3,0.1

Type RM Length L Ch R = 1 ,8535    ,441.6,446.9,449.2
XS GIS Cut Line= 4
2274177.53882623654082.801166645 2274091.7804275653811.303615913
2274018.39087387653752.6788735322273550.03731165653598.338934689
#Sta/Elev= 30
       0 2212.55    26.9 2197.39    47.8 2186.61    77.2 2173.29   169.5 2140.91
   211.4 2124.49   236.6 2117.38   244.7 2114.27   257.6 2106.36   261.8    2103
   273.3 2090.69   278.6 2087.68   291.6 2087.66   300.2 2085.65   334.3  2087.6
  347.84 2083.24   357.1 2082.07  362.03 2083.21   371.4 2087.79   418.9 2086.93
   439.9 2089.19   456.8 2090.01   562.1 2090.07   620.8 2090.95   654.7 2090.19
   696.8 2091.37   747.5 2096.16   779.1 2105.43   831.6 2112.92   871.8 2119.93
#Mann= 5 ,-1,0
       0      .1       0     140     .06       0  324.72     .05       0
  347.84    .045       0  362.03     .05       0
Bank Sta=347.84,362.03
XS Rating Curve= 0 ,0
Exp/Cntr=0.3,0.1

Type RM Length L Ch R = 1 ,8088    ,449.5,449.5,448.8
XS GIS Cut Line= 3
2274450.83750732653845.1588043282274262.62402903653411.506731891
2273872.79794946653270.782050536
#Sta/Elev= 30
       0 2158.17    30.5  2149.1    65.4 2135.98     109 2121.69     151 2105.69
   161.3 2102.38   165.7 2100.17   174.4 2092.47   178.8 2091.53   191.8 2091.71
   214.9 2084.42   230.1 2080.95   248.5  2078.5   348.8 2076.96     376 2074.75
   401.1 2074.77   424.7 2076.11   427.7 2075.62     436  2070.9   444.7 2068.71
   449.1 2069.22  451.28 2070.85   457.8 2075.82   462.2 2076.76   492.1  2076.8
   534.9 2079.28   581.7 2080.31   732.5 2086.97   828.3  2090.1   887.2 2094.13
#Mann= 5 ,-1,0
       0      .1       0     110     .06       0     320     .05       0
     436    .045       0  451.28     .05       0
Bank Sta=436,451.28
XS Rating Curve= 0 ,0
Exp/Cntr=0.3,0.1

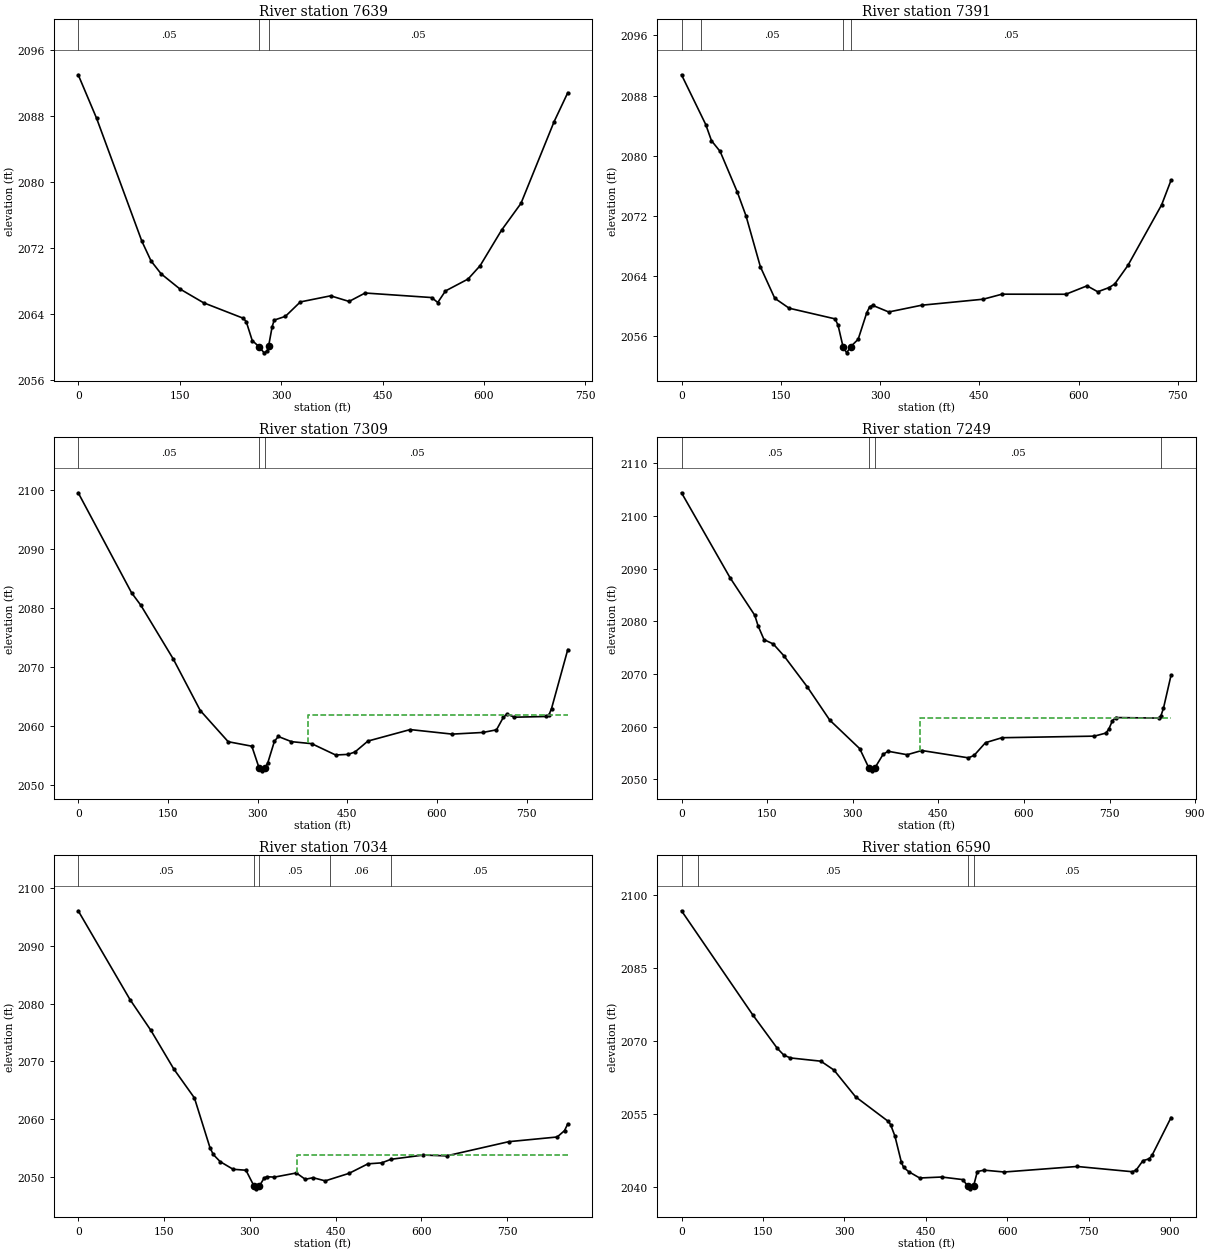
Type RM Length L Ch R = 1 ,7639    ,246.6,248,248
XS GIS Cut Line= 2
2274773.91632861653451.7681776522274452.70432962652803.098390787
#Sta/Elev= 30
       0 2092.99    27.1 2087.74    94.1 2072.85   107.7 2070.46   122.6  2068.9
   150.2 2067.08   185.3  2065.4   243.9 2063.53   248.4 2063.13   257.3 2060.83
   267.1  2060.1   274.9 2059.34   279.6 2059.59  281.42 2060.12   286.8 2062.52
   289.8  2063.3   306.4 2063.76   328.4  2065.5   373.2 2066.24   400.5 2065.56
   424.2 2066.58   522.7 2066.03   531.6 2065.43     543 2066.83   576.4 2068.27
   594.3 2069.89   625.9 2074.18   654.6 2077.42   703.7 2087.33723.8436 2090.82
#Mann= 3 ,-1,0
       0     .05       0   267.1    .045       0  281.42     .05       0
Bank Sta=267.1,281.42
XS Rating Curve= 0 ,0
Exp/Cntr(USF)=0,0
Exp/Cntr=0.3,0.1

Type RM Length L Ch R = 1 ,7391    ,82,81.8,81.6
XS GIS Cut Line= 3
2274984.70603933 653378.894509552274871.52714387653112.539516258
2274527.02760409652822.184334411
#Sta/Elev= 30
       0 2090.76    36.6 2084.14    45.3 2081.98    58.4 2080.55    84.4 2075.13
    97.5 2071.97   119.2  2065.2   140.9 2061.01   162.7 2059.68   232.2 2058.26
   236.6 2057.41   244.1 2054.56   249.6 2053.74  255.79 2054.57     267 2055.55
     280 2059.09   284.4 2059.87   288.7 2060.07   313.2 2059.18   362.9 2060.08
     456 2060.88   484.4 2061.55   580.9 2061.54   612.9 2062.66   629.1 2061.87
   646.2 2062.43   654.7  2062.9   674.6 2065.37   725.6 2073.44   739.9 2076.73
#Mann= 4 ,-1,0
       0     .06       0      30     .05       0   244.1    .045       0
  255.79     .05       0
Bank Sta=244.1,255.79
XS Rating Curve= 0 ,0
Exp/Cntr=0.3,0.1

Type RM Length L Ch R = 1 ,7309    ,59.6,59.6,59.6
XS GIS Cut Line= 5
 2275146.6020849653355.1750959112274995.49782356 653188.96040844
 2274932.0340338653051.4555306232274929.01194857652997.057996541
2274605.91782509652782.061290604
#Sta/Elev= 30
       0 2099.56    89.2  2082.6   104.7 2080.48   158.9 2071.37   204.2 2062.61
   250.8 2057.33   290.3 2056.57   302.3 2052.93   308.1 2052.39   312.5 2052.94
   316.9 2053.71     328 2057.38   334.5 2058.22   356.6 2057.34   390.4    2057
   430.4 2055.08   451.3 2055.18   462.8 2055.59   484.4 2057.44   555.1 2059.39
   625.3 2058.62   676.6  2058.9   699.4 2059.35   710.9 2061.47   716.7 2062.01
   729.5 2061.49     783 2061.61   787.1 2061.88   791.4 2062.94   818.6 2072.96
#Mann= 3 ,-1,0
       0     .05       0   302.3    .045       0   312.5     .05       0
#XS Ineff= 2 , 0
                          383.66         2061.93
Permanent Ineff=
       F       F
Bank Sta=302.3,312.5
XS Rating Curve= 0 ,0
Exp/Cntr(USF)=0,0
Exp/Cntr=0.3,0.1

Type RM Length L Ch R = 1 ,7249    ,215,215,214.6
XS GIS Cut Line= 5
2275210.82139597653352.1530106852275059.71713463653185.938323213
2274996.25334487653048.4334453962274993.23125964652994.035911314
 2274637.2148892652757.684234383
#Sta/Elev= 30
       0 2104.39    85.1 2088.25   128.4 2081.12   134.2 2079.11   144.6  2076.5
   160.8 2075.67   179.5 2073.42   220.3 2067.54   259.8 2061.21   312.3 2055.79
   328.5 2052.09   333.4 2051.58   338.7 2052.11   353.2  2054.7     362  2055.3
   395.4 2054.64     421 2055.44   502.7 2054.05   512.7 2054.51   532.7 2056.93
   561.5 2057.87   723.4 2058.17   743.6 2058.75   748.7 2059.48   755.1 2061.09
   760.9  2061.7   835.9  2061.6   839.9 2061.96   844.6 2063.49   857.9 2069.76
#Mann= 4 ,-1,0
       0     .05       0   328.5    .045       0   338.7     .05       0
  840.56      .1       0
#XS Ineff= 2 , 0
                          418.59         2061.61
Permanent Ineff=
       F       F
Bank Sta=328.5,338.7
XS Rating Curve= 0 ,0
Exp/Cntr(USF)=0,0
Exp/Cntr=0.3,0.1

Type RM Length L Ch R = 1 ,7034    ,443.9,444,443.5
XS GIS Cut Line= 3
2275342.29980223653257.4346617972275126.61360434652842.520995758
2274742.46410533652785.823375089
#Sta/Elev= 30
       0  2096.1    90.5 2080.73   127.1 2075.38   167.1  2068.7   203.2 2063.68
   230.3 2055.09   236.1 2053.89   248.2 2052.65   270.8 2051.33   293.3 2051.16
  307.492048.401   311.4 2047.94  316.612048.402   324.9 2049.79   329.4 2050.04
     343 2049.97   381.4 2050.69     397 2049.59   410.5 2049.87   431.9 2049.32
   473.7 2050.63   506.5 2052.27   530.7 2052.44   546.9 2053.06   603.5 2053.79
     644 2053.65   752.8 2056.11   837.4 2056.92   850.2 2058.02   855.9  2059.2
#Mann= 5 ,-1,0
       0     .05       0  307.49    .045       0  316.61     .05       0
     440     .06       0  547.63     .05       0
#XS Ineff= 2 , 0
                          381.88         2053.83
Permanent Ineff=
       F       F
Bank Sta=307.49,316.61
XS Rating Curve= 0 ,0
Exp/Cntr=0.3,0.1

Type RM Length L Ch R = 1 ,6590    ,464,466.7,468.9
XS GIS Cut Line= 4
2275569.17020306653189.0565868852275536.72707969 652780.51875353
2275450.26185193652644.710405267 2275134.6435935652545.024605286
#Sta/Elev= 30
       0  2096.8   130.9 2075.45   176.4 2068.52   188.5 2067.12   200.5 2066.54
   256.7 2065.87   280.8 2064.05   320.5 2058.56   381.1 2053.47   385.1 2052.83
   393.1 2050.47   405.1 2045.04   409.2 2044.02   418.5 2043.15   438.7 2041.85
   479.3 2042.05   518.1 2041.52   527.6 2040.15   532.3 2039.62  537.88 2040.15
   544.9 2043.18   557.5 2043.46   594.4 2043.08   728.6 2044.22   830.3 2043.14
   837.3 2043.45   849.9  2045.4   861.5  2045.8   866.6 2046.48   901.8 2054.29
#Mann= 4 ,-1,0
       0     .06       0      30     .05       0   527.6    .045       0
  537.88     .05       0
Bank Sta=527.6,537.88
XS Rating Curve= 0 ,0
Exp/Cntr=0.3,0.1

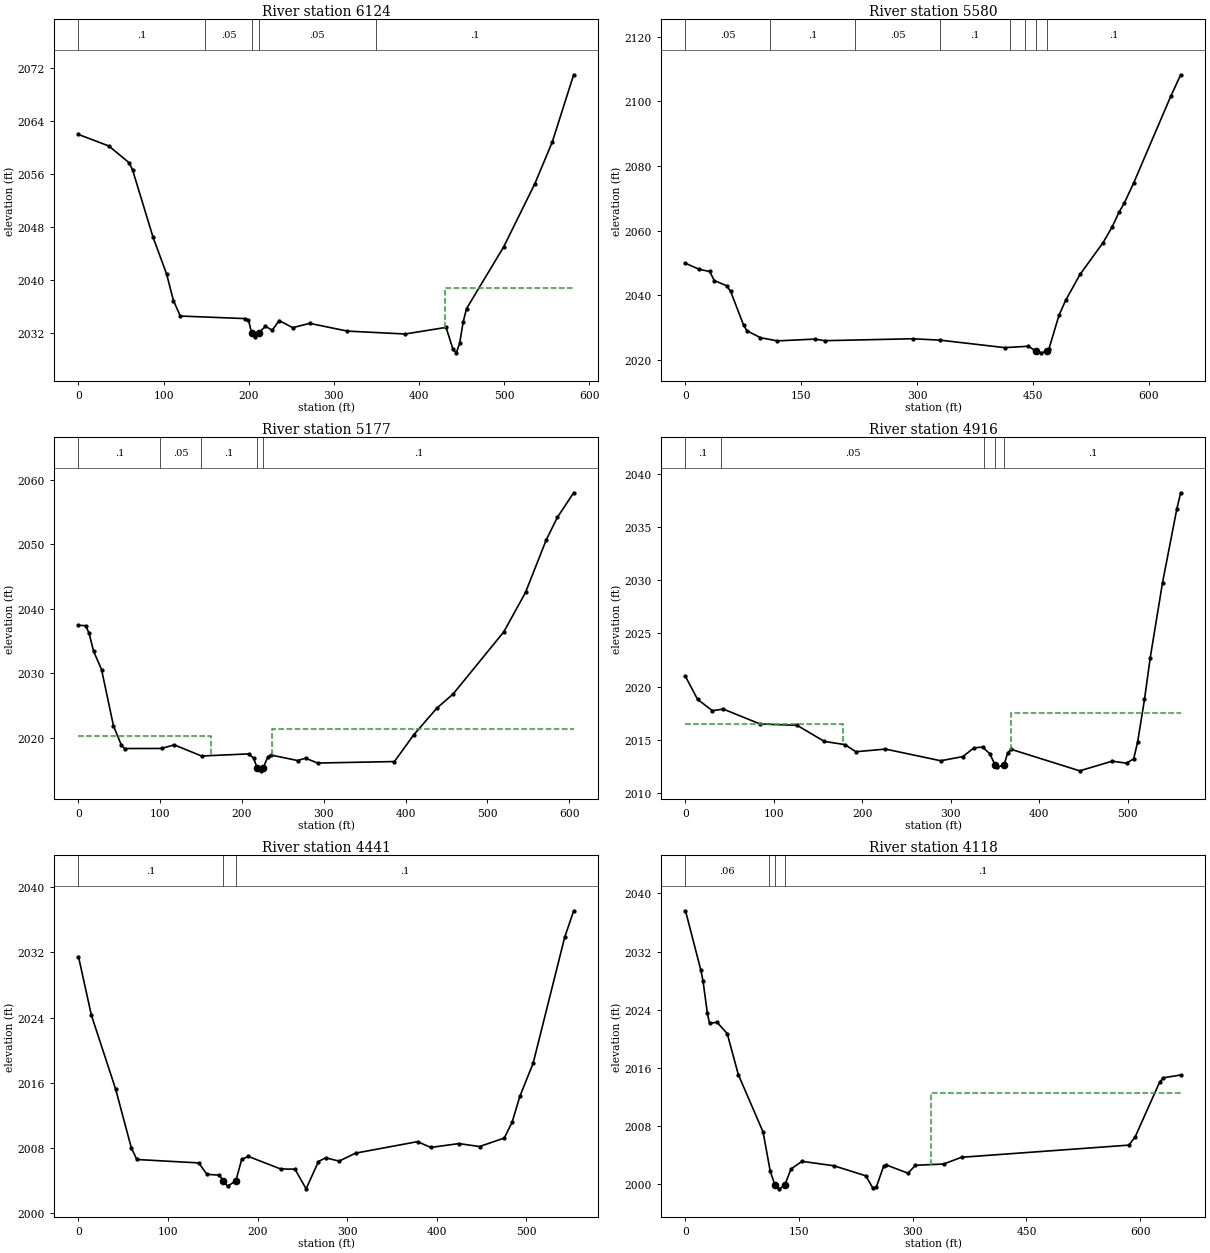
Type RM Length L Ch R = 1 ,6124    ,534.3,543.4,541.9
XS GIS Cut Line= 4
2275889.46983368652816.7077876662275893.31330798652707.907360288
2275887.23913594652537.3865721352275871.42841904652235.491670499
#Sta/Elev= 30
       0 2061.98    35.6 2060.24    59.6 2057.69    63.6 2056.59    87.6 2046.44
   103.6 2040.83   111.6 2036.83   119.6 2034.51   195.7 2034.12   199.7 2033.93
  203.37 2031.96   207.7 2031.33   211.7 2031.97   219.7 2032.95   227.7 2032.36
   235.7 2033.83   251.7 2032.75   271.7  2033.4   315.8 2032.23   383.8 2031.79
   431.9 2032.79   439.9 2029.51   443.9 2028.94   447.9  2030.4   451.9 2033.57
   455.9 2035.62   499.6 2044.98   536.1  2054.5   556.7 2060.85   581.8 2071.01
#Mann= 5 ,-1,0
       0      .1       0  148.87     .05       0  203.37    .045       0
   211.7     .05       0   349.5      .1       0
#XS Ineff= 2 , 0
                          430.41         2038.77
Permanent Ineff=
       F       F
Bank Sta=203.37,211.7
XS Rating Curve= 0 ,0
Exp/Cntr=0.3,0.1

Type RM Length L Ch R = 1 ,5580    ,399.7,402.8,402.7
XS GIS Cut Line= 3
2276155.20288052652865.6056370362276358.54736089652418.175041338
2276360.00103778652268.303185952
#Sta/Elev= 30
       0 2049.88      18 2047.98    31.2 2047.35    37.3 2044.54    53.2 2042.93
    58.5 2041.18    75.2 2030.75    79.6    2029    97.1 2026.86   118.9 2025.87
   167.4 2026.42   180.6 2025.93   294.1 2026.53     330 2026.09   413.5 2023.78
   444.2 2024.21  454.132022.621   460.2 2022.17  467.772022.622   470.6  2023.3
   483.8 2033.84   492.5 2038.48     511 2046.43   540.5 2056.16   552.5 2061.09
   561.4 2065.63   568.5 2068.59   580.5 2074.75   628.5 2101.55   641.3 2108.19
#Mann= 8 ,-1,0
       0     .05       0     110      .1       0     220     .05       0
     330      .1       0     420     .05       0     440      .1       0
  454.13    .045       0  467.77      .1       0
Bank Sta=454.13,467.77
XS Rating Curve= 0 ,0
Exp/Cntr=0.3,0.1

Type RM Length L Ch R = 1 ,5177    ,263.5,261.9,260
XS GIS Cut Line= 3
2276536.75322058652848.1972841452276801.61540083652472.263867016
2276772.32188781652329.457991029
#Sta/Elev= 30
       0 2037.47     8.6 2037.41    12.9 2036.28    18.4 2033.47    28.2 2030.61
    42.8 2021.87    52.6 2018.84    56.3 2018.36   101.6 2018.37   117.1 2018.93
   150.5  2017.2   208.4 2017.53   214.2 2016.84  218.432015.398   222.8  2014.9
  226.012015.398   231.4    2017   235.1 2017.36   267.9  2016.5   277.7 2016.86
   292.4 2016.11   386.4 2016.34   409.8 2020.45   438.1  2024.6   458.2 2026.82
   520.2 2036.46   546.7 2042.56   572.1 2050.73   585.7 2054.21   605.6 2058.02
#Mann= 5 ,-1,0
       0      .1       0     100     .05       0     150      .1       0
  218.43    .045       0  226.01      .1       0
#XS Ineff= 2 , 0
           162.2 2020.36  237.03         2021.43
Permanent Ineff=
       F       F
Bank Sta=218.43,226.01
XS Rating Curve= 0 ,0
Exp/Cntr(USF)=0,0
Exp/Cntr=0.3,0.1

Type RM Length L Ch R = 1 ,4916    ,476.4,474.8,465.2
XS GIS Cut Line= 3
 2276587.0601463652865.2133673872276901.55891515652773.392087705
2276945.01955482652544.976802464
#Sta/Elev= 30
       0 2020.95    13.7 2018.79    30.3 2017.73    42.9 2017.87    84.5 2016.47
   126.2 2016.35   157.1 2014.83   180.3 2014.53   192.8 2013.86   226.2 2014.11
   288.7 2013.01   313.7  2013.4   326.2 2014.22     336  2014.3   344.1 2013.68
  350.07 2012.65   352.3 2012.39   360.4 2012.63   364.5 2013.77   368.6 2014.08
   445.9 2012.06   482.6 2012.97   498.9 2012.78     507  2013.2   511.4 2014.77
   519.2 2018.79   525.7 2022.72   539.6 2029.79   555.8 2036.74   560.1 2038.25
#Mann= 5 ,-1,0
       0      .1       0      40     .05       0  337.63      .1       0
  350.07    .045       0   360.4      .1       0
#XS Ineff= 2 , 0
          177.97  2016.5  368.45         2017.54
Permanent Ineff=
       F       F
Bank Sta=350.07,360.4
XS Rating Curve= 0 ,0
Exp/Cntr(USF)=0,0
Exp/Cntr=0.3,0.1

Type RM Length L Ch R = 1 ,4441    ,320.7,322.7,320.5
XS GIS Cut Line= 2
2277376.28614098652957.6528617242277101.60782657652477.966825776
#Sta/Elev= 30
       0 2031.47    14.4 2024.29    41.5 2015.21      59 2008.01    65.1 2006.59
   134.2 2006.17   143.4 2004.77   157.3 2004.67  161.32    2004   166.5  2003.3
   175.7 2003.99   182.2  2006.6   189.5 2006.97   225.6 2005.43   241.7  2005.4
   254.1 2002.99   267.9 2006.34   275.9  2006.8   290.9 2006.39   309.4 2007.37
   378.5 2008.78   393.2 2008.07   424.6 2008.54   447.7 2008.18   475.3 2009.22
     484 2011.15   492.8 2014.36   507.6 2018.43   542.7 2033.83552.7629  2037.1
#Mann= 3 ,-1,0
       0      .1       0  161.32    .045       0   175.7      .1       0
Bank Sta=161.32,175.7
XS Rating Curve= 0 ,0
Exp/Cntr(USF)=0,0
Exp/Cntr=0.3,0.1

Type RM Length L Ch R = 1 ,4118    ,360.5,360.7,357.5
XS GIS Cut Line= 2
2277636.30064644652856.7807322232277297.83510687 652297.73407946
#Sta/Elev= 30
       0 2037.61    20.2 2029.48    23.1 2027.98    28.9 2023.52    31.8 2022.12
    41.6 2022.29    55.1 2020.72    69.7 2015.09   102.4  2007.2   111.8 2001.83
  118.26 1999.84   123.8 1999.38   130.9 1999.86   139.3 2002.12   153.8 2003.16
   195.9 2002.55     238 2001.17   247.4 1999.47     252 1999.66   261.4 2002.47
   264.8 2002.67   293.7 2001.53   303.5 2002.62   340.6 2002.79   364.3 2003.72
   585.2 2005.39   593.4 2006.51   625.8 2014.06   630.8 2014.65653.5228 2015.03
#Mann= 4 ,-1,0
       0     .06       0     110      .1       0  118.26    .045       0
   130.9      .1       0
#XS Ineff= 2 , 0
                          323.88         2012.56
Permanent Ineff=
       F       F
Bank Sta=118.26,130.9
XS Rating Curve= 0 ,0
Exp/Cntr(USF)=0,0
Exp/Cntr=0.3,0.1

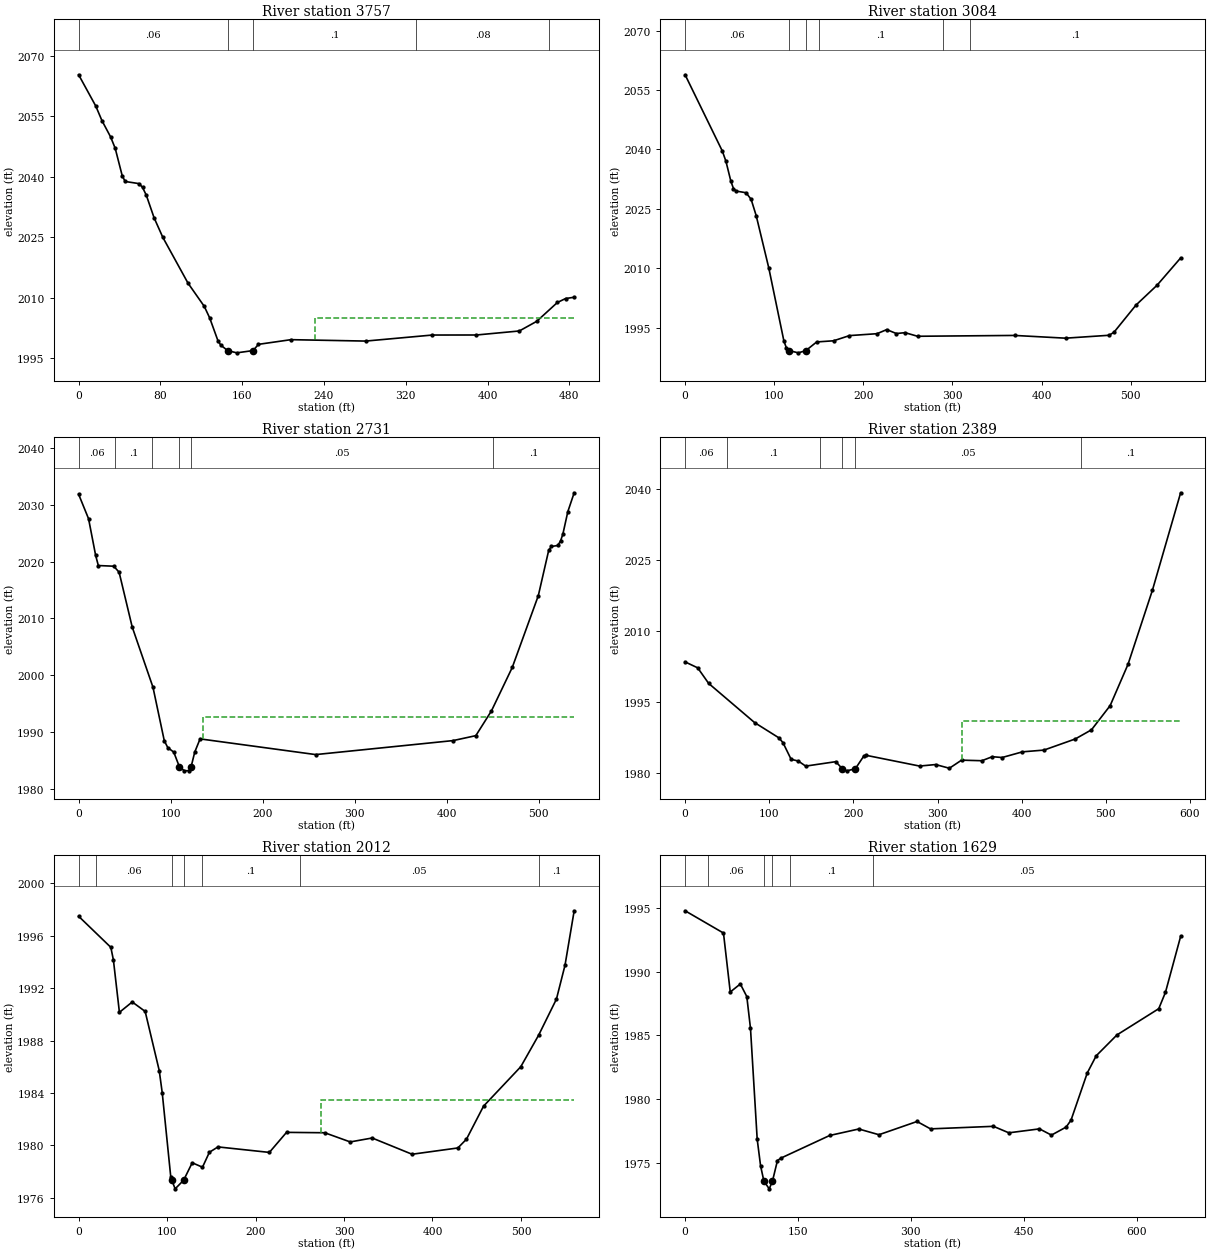
Type RM Length L Ch R = 1 ,3757    ,666.7,672.8,666
XS GIS Cut Line= 2
2277852.86696774652580.653452465 2277487.2224058652262.410503159
#Sta/Elev= 30
       0 2065.34    16.8 2057.56    22.8 2053.96    31.3  2049.9    35.8 2047.06
    42.6 2040.31    45.5 2038.85    59.2 2038.31    62.5 2037.38    66.2 2035.44
    73.8 2029.84    82.3    2025     107  2013.6   122.9 2007.84   128.2 2004.97
   136.2 1999.36     139 1998.22  145.74 1996.86   154.7  1996.3   170.6 1996.86
   175.9 1998.41   207.7 1999.57   280.8 1999.22     346 2000.72   389.1 2000.73
   431.1 2001.73   448.1 2004.12   468.3  2008.8   476.4 2009.79484.7417  2010.1
#Mann= 5 ,-1,0
       0     .06       0  145.74    .045       0   170.6      .1       0
     330     .08       0     460      .1       0
#XS Ineff= 2 , 0
                          231.13         2005.01
Permanent Ineff=
       F       F
Bank Sta=145.74,170.6
XS Rating Curve= 0 ,0
Exp/Cntr(USF)=0,0
Exp/Cntr=0.3,0.1

Type RM Length L Ch R = 1 ,3084    ,352.4,353.6,353.2
XS GIS Cut Line= 2
2278234.99301084652275.030961633 2277824.9715977651899.279994967
#Sta/Elev= 30
       0 2058.84    41.8 2039.59    45.8 2037.04    51.4 2031.96    54.3 2030.15
    57.1 2029.51    68.4 2029.08    74.1 2027.42    79.8  2023.3    93.9 2010.13
   110.9 1991.66   113.7 1989.92   116.5 1989.26   127.1 1988.69  135.43 1989.24
   147.7 1991.44   166.6 1991.73   184.5 1993.04   215.4 1993.52   226.3 1994.55
   237.1 1993.56   246.8 1993.78   260.9 1992.87   369.8 1993.08     427 1992.39
   475.8 1993.12   481.3 1993.87     506 2000.73   529.7 2005.75556.1532 2012.63
#Mann= 6 ,-1,0
       0     .06       0   116.5    .045       0  135.43     .06       0
     150      .1       0     290     .05       0     320      .1       0
Bank Sta=116.5,135.43
XS Rating Curve= 0 ,0
Exp/Cntr(USF)=0,0
Exp/Cntr=0.3,0.1

Type RM Length L Ch R = 1 ,2731    ,340.8,342.2,344.5
XS GIS Cut Line= 2
2278446.48005841652009.0713631062278078.07275884651616.185173204
#Sta/Elev= 30
       0 2031.83    10.8 2027.53    18.5 2021.08    21.4  2019.3    38.2 2019.18
      44 2018.12    58.2  2008.5    80.8 1997.89    93.1 1988.47    96.9 1987.27
   103.4 1986.47   109.5  1983.9     115 1983.18   120.5 1983.23  122.25 1983.89
   126.2 1986.48     132  1988.8   257.6 1986.04   406.9  1988.5   431.7 1989.37
   448.7 1993.73   471.3 2001.37   499.6 2013.99   510.9 2021.97   513.8 2022.65
   520.8 2022.83   523.8 2023.63   526.3 2024.82   531.7 2028.78 538.594  2032.1
#Mann= 6 ,-1,0
       0     .06       0      40      .1       0      80     .05       0
   109.5    .045       0  122.25     .05       0     450      .1       0
#XS Ineff= 2 , 0
                          135.33         1992.74
Permanent Ineff=
       F       F
Bank Sta=109.5,122.25
XS Rating Curve= 0 ,0
Exp/Cntr(USF)=0,0
Exp/Cntr=0.3,0.1

Type RM Length L Ch R = 1 ,2389    ,372.5,376.5,371.7
XS GIS Cut Line= 2
2278654.57311511651817.6467005732278325.33204009651329.292838359
#Sta/Elev= 30
       0 2003.45      15 2002.19      28  1998.9    82.6 1990.61   111.5 1987.38
   116.3 1986.37     126 1982.84   134.6 1982.47   143.3  1981.4   179.1 1982.34
  186.891980.839   192.2  1980.4  202.321980.838   212.4 1983.53   215.3 1983.68
   278.7 1981.41   297.7 1981.73   314.1 1980.95   328.6 1982.66   352.7 1982.54
   365.1 1983.39   376.8 1983.22     401 1984.42   426.5 1984.79   463.7 1987.14
     483 1989.08   505.2  1994.2   526.4 2002.92   555.5 2018.65 588.973 2039.23
#Mann= 6 ,-1,0
       0     .06       0      50      .1       0     160     .05       0
  186.89    .045       0  202.32     .05       0     470      .1       0
#XS Ineff= 2 , 0
                          329.34         1991.01
Permanent Ineff=
       F       F
Bank Sta=186.89,202.32
XS Rating Curve= 0 ,0
Exp/Cntr(USF)=0,0
Exp/Cntr=0.3,0.1

Type RM Length L Ch R = 1 ,2012    ,385.2,382.9,379.3
XS GIS Cut Line= 2
2278884.67468428 651695.252248892278568.89699894651232.601221529
#Sta/Elev= 30
       0 1997.49    36.4 1995.12    39.3 1994.16    46.1 1990.16    60.6 1990.95
    75.2 1990.23    91.1 1985.72    94.5 1984.02   104.2 1977.56  105.29 1977.35
   109.1 1976.69   118.7 1977.35   128.4 1978.68     140 1978.34   147.8 1979.48
   157.5 1979.89   215.6 1979.47     235    1981   278.2 1980.97     307 1980.27
   331.8 1980.57   376.9 1979.33   428.7 1979.81   438.4 1980.48   457.7    1983
   499.8 1986.01     520 1988.42   540.1 1991.17   549.8 1993.76560.1442 1997.91
#Mann= 7 ,-1,0
       0      .1       0      20     .06       0  105.29    .045       0
   118.7     .06       0     140      .1       0     250     .05       0
     520      .1       0
#XS Ineff= 2 , 0
                          274.39         1983.45
Permanent Ineff=
       F       F
Bank Sta=105.29,118.7
XS Rating Curve= 0 ,0
Exp/Cntr(USF)=0,0
Exp/Cntr=0.3,0.1

Type RM Length L Ch R = 1 ,1629    ,201.5,200,197.8
XS GIS Cut Line= 2
2279201.67631414651501.8690152312278614.18294606651204.450497642
#Sta/Elev= 30
       0 1994.79      51 1993.04      60 1988.41    73.4 1989.04      82 1988.05
    86.9 1985.55    95.8 1976.85   100.3 1974.76  104.711973.555   111.8 1972.95
   116.11973.554   122.7 1975.17   127.2 1975.36   192.1 1977.14   230.8 1977.65
   257.6  1977.2   308.2 1978.24   326.1 1977.66   409.7 1977.86   430.2 1977.35
   470.9 1977.66   486.8 1977.17   506.3  1977.8   512.8 1978.34   534.4 1982.05
   546.3  1983.4   573.9 1985.04   629.4  1987.1   638.3 1988.38658.4879 1992.78
#Mann= 6 ,-1,0
       0     .05       0      30     .06       0  104.71    .045       0
   116.1     .06       0     140      .1       0     250     .05       0
Bank Sta=104.71,116.1
XS Rating Curve= 0 ,0
Exp/Cntr(USF)=0,0
Exp/Cntr=0.3,0.1

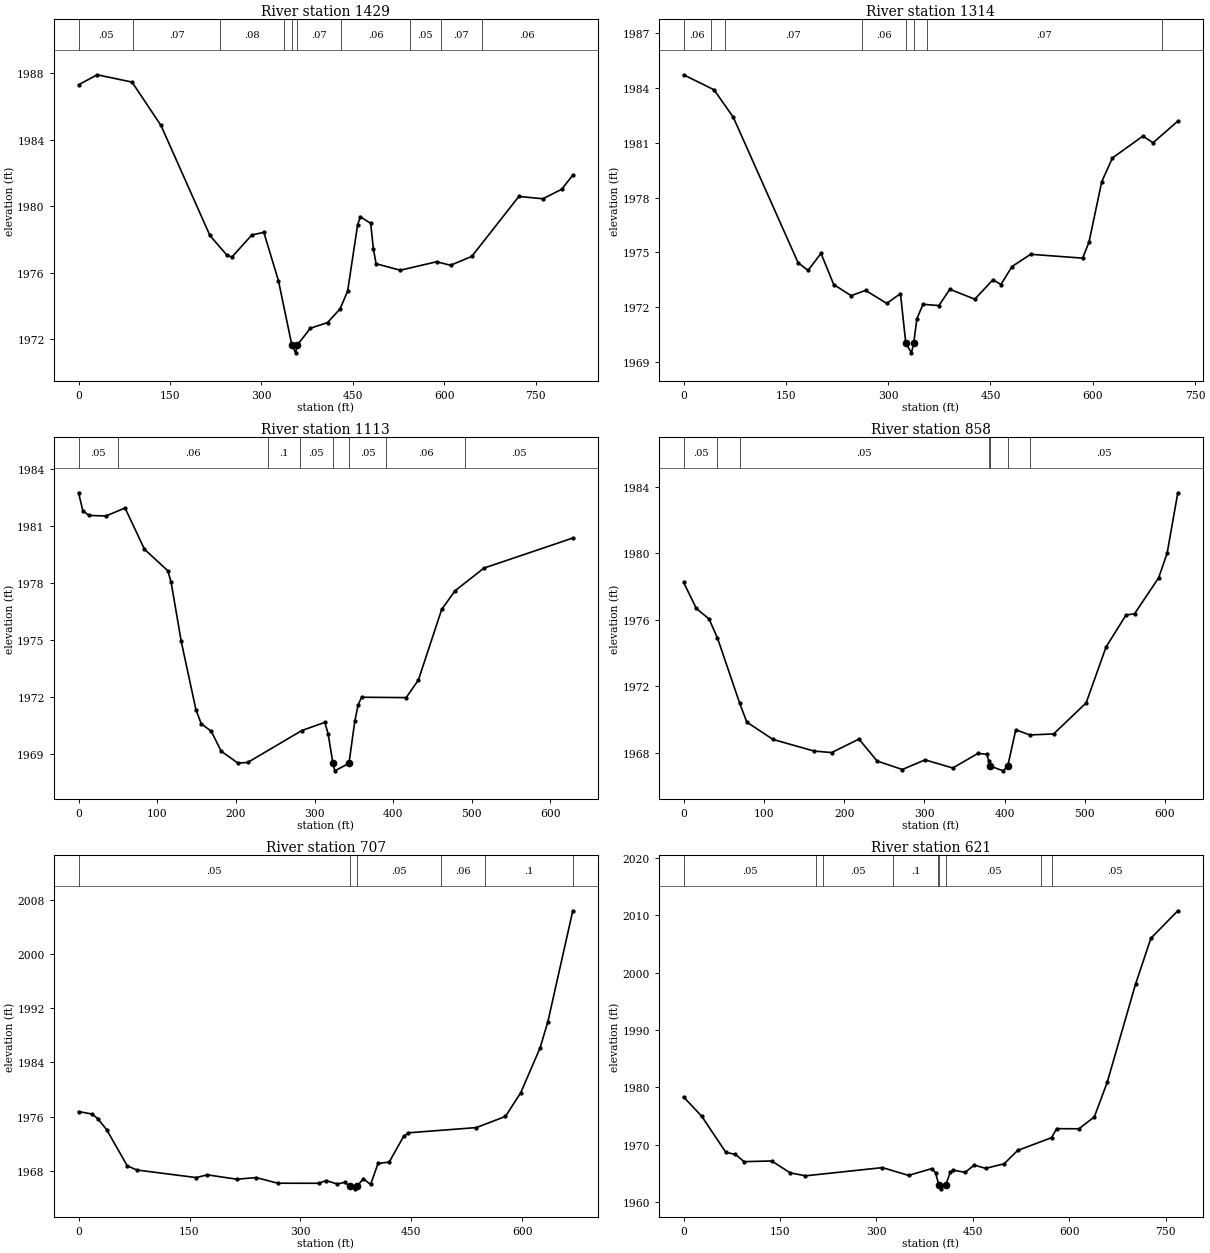
Type RM Length L Ch R = 1 ,1429    ,116.2,114.9,115.1
XS GIS Cut Line= 6
2279510.57033485651301.8647333092279101.89526068651261.107380899
 2279041.3100071651244.5841299222278911.32709941651175.186475817
2278852.94494596651109.0934719092278811.08604348651016.563266437
#Sta/Elev= 30
       0  1987.3    30.6  1987.9    87.7 1987.46   135.2 1984.85   215.5 1978.23
   243.7 1977.03   251.7 1976.94   284.2 1978.26   303.9 1978.42   327.9 1975.51
  349.951971.624   356.2 1971.17  358.471971.625   380.3 1972.65   408.4 1972.99
   429.1 1973.82   441.4 1974.89   457.7 1978.86   462.2 1979.36   479.2 1978.96
   483.7  1977.4   488.1 1976.53   527.8 1976.14   587.4 1976.65   610.2 1976.44
     645 1976.97   722.3 1980.58   761.8 1980.44   792.5 1981.01810.7347 1981.86
#Mann= 10 ,-1,0
       0     .05       0      90     .07       0  231.91     .08       0
  336.69     .07       0  349.95    .045       0  358.47     .07       0
  430.71     .06       0  543.51     .05       0   594.3     .07       0
  660.99     .06       0
Bank Sta=349.95,358.47
XS Rating Curve= 0 ,0
Exp/Cntr(USF)=0,0
Exp/Cntr=0.3,0.1

Type RM Length L Ch R = 1 ,1314    ,199.3,201,204.2
XS GIS Cut Line= 6
2279532.60133615 651197.217477122279123.92626198 651156.46012471
 2279063.3410084651139.9368737332278933.35810071651070.539219629
2278906.92089915 651040.797367872278872.77284713650986.821414678
#Sta/Elev= 30
       0  1984.7    44.7 1983.88    72.9 1982.38   167.9 1974.44   182.5 1974.02
   201.5 1974.95   220.1 1973.25   245.7 1972.64   266.8 1972.93   297.9 1972.22
     318 1972.75  325.83 1970.05   334.1 1969.52  337.44 1970.05   342.1 1971.39
   351.1 1972.17   374.3  1972.1   390.4 1972.99     427 1972.45   453.6 1973.51
   465.3 1973.25   481.5 1974.23   508.9  1974.9   585.1 1974.69   594.4 1975.56
   613.1 1978.86   628.8 1980.16   673.4 1981.35   688.4 1980.99 724.655 1982.17
#Mann= 8 ,-1,0
       0     .06       0      40     .05       0      60     .07       0
  261.91     .06       0  325.83    .045       0  337.44     .06       0
  356.69     .07       0  700.78     .06       0
Bank Sta=325.83,337.44
XS Rating Curve= 0 ,0
Exp/Cntr(USF)=0,0
Exp/Cntr=0.3,0.1

Type RM Length L Ch R = 1 ,1113    ,253.4,255.1,260.7
XS GIS Cut Line= 4
2279506.16413459651125.6167228862279447.78198114   651043.000468
2279079.86425938650911.916010248 2278943.2720513650909.712910118
#Sta/Elev= 30
       0 1982.74     5.4  1981.8    13.2 1981.55    34.8 1981.52    59.1 1981.94
    83.8 1979.77   113.5 1978.64   117.7 1978.03   130.5 1974.93   149.2 1971.34
   155.9  1970.6   168.7  1970.2   181.4 1969.15   202.5 1968.53     215 1968.56
   283.9 1970.24   313.1 1970.67   317.3 1970.06  323.371968.515   325.8 1968.12
   343.81968.515   351.3 1970.76   355.5 1971.59   359.8 1971.99   416.5 1971.97
     432 1972.89   461.7 1976.61   478.7 1977.59   515.4 1978.78 628.345 1980.36
#Mann= 8 ,-1,0
       0     .05       0      50     .06       0  241.16      .1       0
  281.16     .05       0  323.37    .045       0   343.8     .05       0
  391.16     .06       0  491.16     .05       0
Bank Sta=323.37,343.8
XS Rating Curve= 0 ,0
Exp/Cntr(USF)=0,0
Exp/Cntr=0.3,0.1

Type RM Length L Ch R = 1 ,858     ,147.2,150.9,151.5
XS GIS Cut Line= 2
2279700.34490388651041.0846042272279229.98302607650643.425030709
#Sta/Elev= 30
       0 1978.26    15.9 1976.69    31.7 1976.06    42.1 1974.93      70 1970.98
    78.8 1969.85   111.4 1968.81   162.6 1968.11   184.5 1968.02   218.6 1968.83
   241.2 1967.51   272.6    1967   300.9 1967.58   335.5 1967.09   366.9 1967.97
   377.6 1967.92   380.4 1967.53  381.98 1967.21   398.3 1966.92     404 1967.21
     414 1969.39   431.5 1969.08   461.2 1969.14   501.7 1971.01   526.5 1974.37
   551.3 1976.29     562 1976.37   592.1 1978.54   602.6 1980.01 615.933 1983.65
#Mann= 7 ,-1,0
       0     .05       0    42.1     .06       0      70     .05       0
   380.4      .1       0  381.98    .045       0     404      .1       0
   431.5     .05       0
Bank Sta=381.98,404
XS Rating Curve= 0 ,0
Exp/Cntr(USF)=0,0
Exp/Cntr=0.3,0.1

Type RM Length L Ch R = 1 ,707     ,84.8,85.8,85.8
XS GIS Cut Line= 4
2279706.82650268650994.8297983982279699.90591023650939.465058785
2279455.70786229650617.1631817492279274.78380248650514.342951039
#Sta/Elev= 30
       0 1976.75    18.2 1976.39    25.9 1975.72    37.9 1974.09    65.8 1968.76
    78.7 1968.14     159 1967.02   174.1 1967.42     214 1966.78     240 1967.02
   269.4 1966.19   324.6 1966.18   334.7 1966.58   349.7 1966.08   359.8 1966.31
  367.221965.732   373.3 1965.36  376.631965.733   384.9 1966.85   394.9    1966
   404.9  1969.1     420  1969.3   439.5 1973.09   446.1 1973.62   537.8 1974.39
   577.2 1976.03   597.8 1979.51   624.1 1986.16   634.5 1989.97668.2606 2006.35
#Mann= 6 ,-1,0
       0     .05       0  367.22    .045       0  376.63     .05       0
  490.16     .06       0  550.16      .1       0  668.26     .05       0
Bank Sta=367.22,376.63
XS Rating Curve= 0 ,0
Exp/Cntr(USF)=0,0
Exp/Cntr=0.3,0.1

Type RM Length L Ch R = 1 ,621     ,66,65.8,65.6
XS GIS Cut Line= 4
2279749.77930052650981.4983307562279740.96689999650895.577425675
2279473.29023416650488.0039015712279278.31587263650483.597701311
#Sta/Elev= 30
       0 1978.31    28.5 1974.91    65.8 1968.64    80.7  1968.3      94 1967.03
   137.1 1967.15   165.8 1965.08   189.7 1964.56   309.4 1965.99   350.1 1964.63
   386.2 1965.82     392 1965.11     3971963.035   400.3 1962.29  408.131963.035
   415.1  1965.2   419.4 1965.55   438.2 1965.16   452.1 1966.43     470 1965.86
   498.8 1966.66   519.9 1968.99   572.6 1971.21   580.4 1972.78   615.1 1972.76
   639.1 1974.83   659.1 1980.84   703.2 1997.96   727.1 2005.97769.0093 2010.77
#Mann= 9 ,-1,0
       0     .05       0  206.37      .1       0  216.37     .05       0
  326.37      .1       0  396.37     .05       0     397    .045       0
  408.13     .05       0  556.37      .1       0  573.99     .05       0
Bank Sta=397,408.13
XS Rating Curve= 0 ,0
Exp/Cntr(USF)=0,0
Exp/Cntr=0.3,0.1