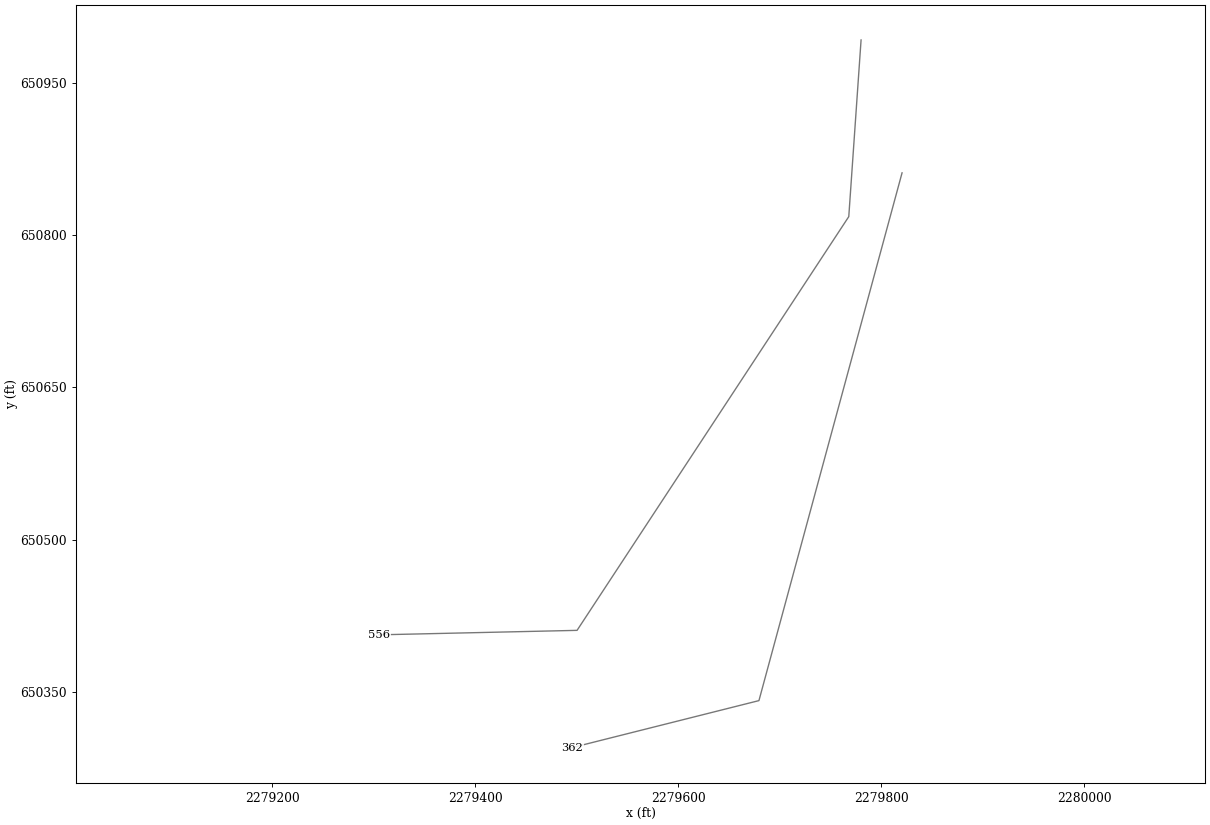
HEC-RAS study TYGVRVT2.prj: TYGVRVT2

--- TYGVRVT2.g01 (geometry) --- (continued)

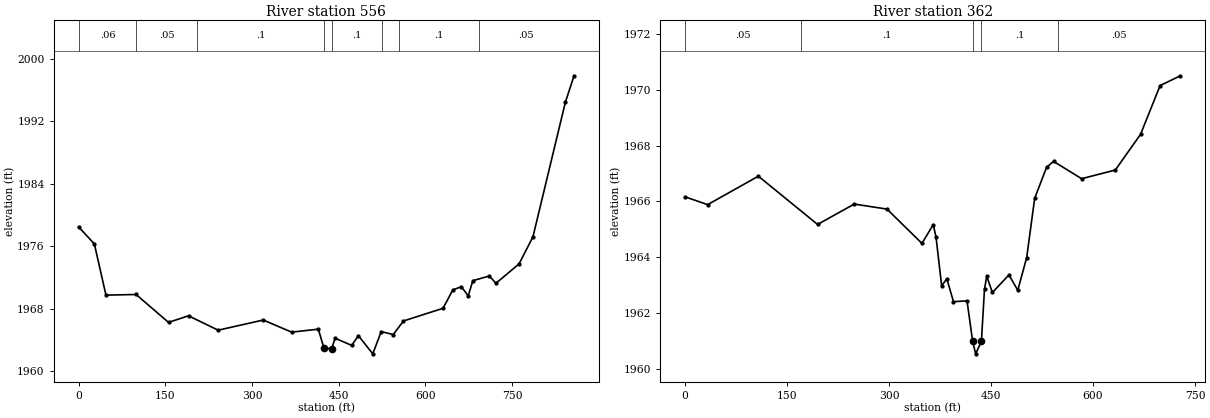
Type RM Length L Ch R = 1 ,556     ,191.3,193.6,195.5
XS GIS Cut Line= 4
2279779.89932578650992.3291650042279767.78227506650818.284254711
2279500.10560923650410.710730607 2279305.1312477650406.304530347
#Sta/Elev= 30
       0 1978.45    27.2 1976.28    47.3 1969.72    99.4  1969.8   155.5 1966.23
   190.1 1967.07   241.4 1965.23   319.4 1966.53   368.5 1964.98   414.7 1965.36
   424.6 1962.89   437.8 1962.88   443.8  1964.2   472.5 1963.28     484 1964.53
   508.9  1962.2   523.5 1965.05   544.3 1964.67     562 1966.41   630.4 1968.03
   647.4 1970.39   662.1  1970.8     674 1969.62     682 1971.57   710.5 1972.17
     722 1971.24     762 1973.72     786 1977.19   842.1 1994.43857.1039 1997.81
#Mann= 8 ,-1,0
       0     .06       0     100     .05       0  204.47      .1       0
   424.6    .045       0   437.8      .1       0  524.47     .05       0
  554.47      .1       0  692.08     .05       0
Bank Sta=424.6,437.8
XS Rating Curve= 0 ,0
Exp/Cntr(USF)=0,0
Exp/Cntr=0.3,0.1

Type RM Length L Ch R = 1 ,362     ,,,
XS GIS Cut Line= 3
2279820.27850469650861.4293736552279679.28009635650341.497742907
2279495.32123547650295.232640171
#Sta/Elev= 30
       0 1966.16    33.4 1965.88   107.9  1966.9     195 1965.17   248.9  1965.9
     297 1965.72   348.4 1964.49     365 1965.16   369.1 1964.72   377.4 1962.97
     385 1963.22   394.8  1962.4   414.7 1962.43  422.941960.981   427.4 1960.53
  435.841960.979   440.4 1962.86   443.7 1963.31     452 1962.73   476.3 1963.36
   489.3 1962.81   502.4 1963.98   514.2 1966.11   531.7 1967.22   541.9 1967.43
   583.2 1966.81   632.7 1967.12   669.8  1968.4   698.6 1970.15728.3984  1970.5
#Mann= 5 ,-1,0
       0     .05       0     170      .1       0  422.94    .045       0
  435.84      .1       0  548.71     .05       0
Bank Sta=422.94,435.84
XS Rating Curve= 0 ,0
Exp/Cntr(USF)=0,0
Exp/Cntr=0.3,0.1
LCMann Table=0

Chan Stop Cuts=-1
Use User Specified Reach Order=0
Composite Channel Slope=5